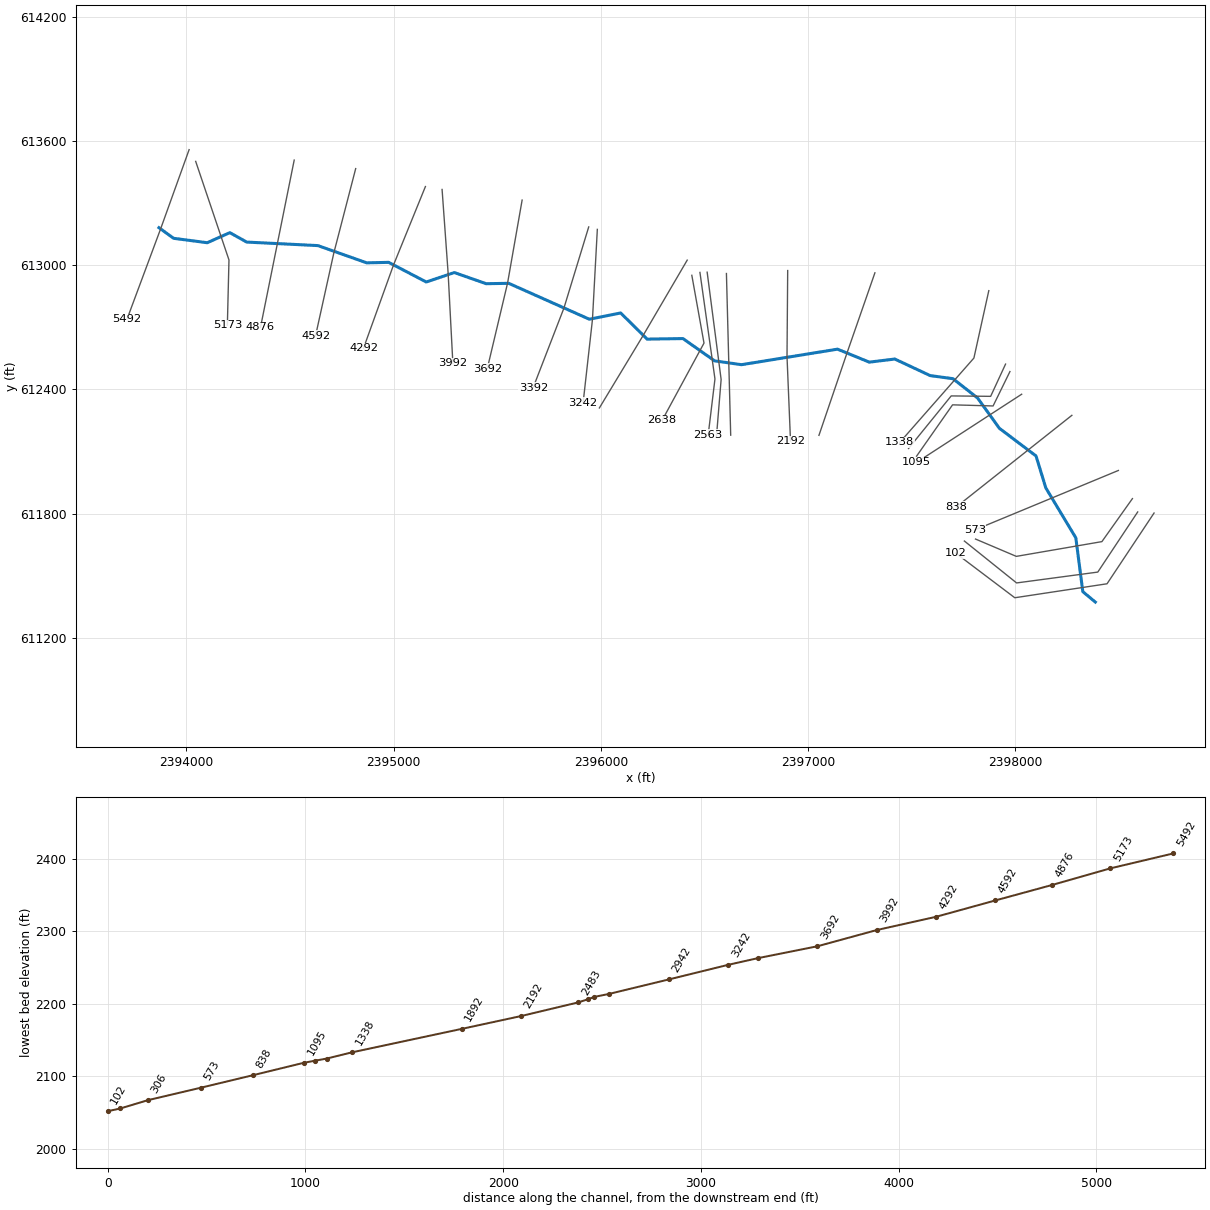
--- BOUSESRN.prj (project) ---

Proj Title=BOUSESRN
Current Plan=p01
Default Exp/Contr=0,0
English Units
Geom File=g01
Flow File=f01
Plan File=p01
BEGIN DESCRIPTION:
Stream Name: Bouses Run
Flood Zone: Approximate
Pendleton County, West Virginia
HEC-RAS Version: 5.0.7
Hydrology Method:
Regression equation
END DESCRIPTION:
DSS Export Rating Curves= 0
DSS Export Rating Curve Sorted= 0
DSS Export Volume Flow Curves= 0
DXF OffsetX= 0
DXF OffsetY= 0
DXF ScaleX= 0
DXF ScaleY= 0

--- BOUSESRN.p01 (plan) ---

Plan Title=Floodplain
Program Version=5.07
Short Identifier=Floodplain
Geom File=g01
Flow File=f01
Subcritical Flow
K Sum by GR= 0
Std Step Tol= 0.01
Critical Tol= 0.01
Num of Std Step Trials= 20
Max Error Tol= 0.3
Flow Tol Ratio= 0.001
Split Flow NTrial= 30
Split Flow Tol= 0.02
Split Flow Ratio= 0.02
Log Output Level= 0
Friction Slope Method= 1
Unsteady Friction Slope Method= 2
Unsteady Bridges Friction Slope Method= 1
Parabolic Critical Depth
Global Vel Dist= 0 , 0 , 0
Global Log Level= 0
CheckData=True
Encroach Param=-1 ,0,0, 0
Mapping Interval=1HOUR
Computation Time Step Use Courant=        0
Computation Time Step Use Time Series=    0
Computation Time Step Count To Double=0
Computation Time Step Max Doubling=0
Computation Time Step Max Halving=0
Computation Time Step Residence Courant=0
Run HTab= 0
Run UNet= 0
Run Sediment= 0
Run PostProcess= 0
Run WQNet= 0
Run RASMapper= 0
UNET Theta= 0
UNET Theta Warmup= 0
UNET ZTol= 0
UNET ZSATol= 0
UNET MxIter= 0
UNET Max Iter WO Improvement= 0
UNET MaxInSteps= 0
UNET DtIC= 0
UNET DtMin= 0
UNET MaxCRTS= 0
UNET WFStab= 0
UNET SFStab= 0
UNET WFX= 1
UNET SFX= 1
UNET 1D Methodology=Finite Difference
UNET DSS MLevel= 1
UNET Pardiso=0
UNET DZMax Abort= 0
UNET Use Existing IB Tables= 0
UNET Froude Reduction=False
UNET Froude Limit= 0
UNET Froude Power= 0
UNET D1 Cores= 0
UNET D2 Coriolis=0
UNET D2 Cores= 0
UNET D2 Theta= 1
UNET D2 Theta Warmup= 1
UNET D2 Z Tol= 0.01
UNET D2 Volume Tol= 0.01
UNET D2 Max Iterations= 20
UNET D2 Equation= 0
UNET D2 RampUpFraction=0.1
UNET D2 TimeSlices= 1
UNET D2 BCVolumeCheck=0
UNET D1D2 MaxIter= 0
UNET D1D2 ZTol=0.01
UNET D1D2 QTol=0.1
UNET D1D2 MinQTol=1
Write IC File= 0
Write IC File at Fixed DateTime=0
Write IC File at Sim End=0
Echo Input=False
Echo Parameters=False
Echo Output=False
Write Detailed= 0
HDF Write Warmup=0
HDF Write Time Slices=0
HDF Flush=0
HDF Face Node Velocities=0
HDF Compression= 1
HDF Chunk Size= 1
HDF Spatial Parts= 1
HDF Use Max Rows=0
HDF Fixed Rows= 1
Calibration Method= 0
Calibration Iterations= 20
Calibration Max Change=0.05
Calibration Tolerance=0.2
Calibration Maximum=1.5
Calibration Minimum=0.5
Calibration Optimization Method= 1
WQ AD Non Conservative
WQ ULTIMATE=-1
WQ Max Comp Step=1HOUR
WQ Output Interval=15MIN
WQ Output Selected Increments= 0
WQ Output face flow=0
WQ Output face velocity=0
WQ Output face area=0
WQ Output face dispersion=0
WQ Output cell volume=0
WQ Output cell surface area=0
WQ Output cell continuity=0
WQ Output cumulative cell continuity=0
WQ Output face conc=0
WQ Output face dconc_dx=0
WQ Output face courant=0
WQ Output face peclet=0
WQ Output face adv mass=0
WQ Output face disp mass=0
WQ Output cell mass=0
WQ Output cell source sink temp=0
WQ Output nsm pathways=0
WQ Output nsm derived pathways=0
WQ Output MaxMinRange=-1
WQ Daily Max Min Mean=-1
WQ Daily Range=0
WQ Daily Time=0
WQ Create Restart=0
WQ Fixed Restart=0
WQ System Summary=0
WQ Write To DSS=0
WQ Use Fixed Temperature=0
Sorting and Armoring Iterations= 10
XS Update Threshold= 0.02
Bed Roughness Predictor= 0
Hydraulics Update Threshold= 0.02
Energy Slope Method= 1
Volume Change Method= 1
Sediment Retention Method= 0
XS Weighting Method= 0
Number of US Weighted Cross Sections= 1
Number of DS Weighted Cross Sections= 1
Upstream XS Weight=0
Main XS Weight=1
Downstream XS Weight=0
Number of DS XS's Weighted with US Boundary= 1
Upstream Boundary Weight= 1
Weight of XSs Associated with US Boundary= 0
Number of US XS's Weighted with DS Boundary= 1
Downstream Boundary Weight= 0.5
Weight of XSs Associated with DS Boundary= 0.5
Percentile Method= 0
Sediment Output Level= 3
Mass or Volume Output= 0
Output Increment Type= 1
Profile and TS Output Increment= 1
XS Output Flag= 0
XS Output Increment= 10
Write Gradation File= 0
Read Gradation Hotstart= 0
Write HDF5 File= 1
Write Binary Output= 1
Write DSS Sediment File= 0
SV Curve= 0
Specific Gage Flag= 0

--- BOUSESRN.f01 (steady flow) ---

Flow Title=Flows
Program Version=5.07
Number of Profiles= 6
Profile Names=P100yr,P10yr,P25yr,P50yr,P500yr,P101yr
River Rch & RM=BOUSESRN,Main            ,5492
     600     281     397     496     881     731
Boundary for River Rch & Prof#=BOUSESRN,Main            , 1
Up Type= 0
Dn Type= 3
Dn Slope=0.05007
Boundary for River Rch & Prof#=BOUSESRN,Main            , 2
Up Type= 0
Dn Type= 3
Dn Slope=0.05007
Boundary for River Rch & Prof#=BOUSESRN,Main            , 3
Up Type= 0
Dn Type= 3
Dn Slope=0.05007
Boundary for River Rch & Prof#=BOUSESRN,Main            , 4
Up Type= 0
Dn Type= 3
Dn Slope=0.05007
Boundary for River Rch & Prof#=BOUSESRN,Main            , 5
Up Type= 0
Dn Type= 3
Dn Slope=0.05007
Boundary for River Rch & Prof#=BOUSESRN,Main            , 6
Up Type= 0
Dn Type= 3
Dn Slope=0.05007
DSS Import GetInterval= 0
DSS Import GetPeak= 0
DSS Import FillOption= 0

--- BOUSESRN.g01 (geometry) ---

Geom Title=Geometry
Program Version=5.07

River Reach=BOUSESRN        ,Main
Reach XY= 30
     2393867.025      613180.943     2393937.773      613129.728
     2394100.111      613108.427     2394209.058      613157.054
     2394290.504      613111.521     2394634.236      613094.536
     2394869.828      613011.342     2394975.964      613013.635
     2395157.051      612918.894     2395292.648      612964.415
     2395446.207      612910.657     2395555.355      612912.408
     2395944.389      612739.129     2396095.592      612769.371
     2396223.166      612643.115     2396396.166      612645.806
     2396548.834       612538.23     2396678.603      612519.708
     2397142.148      612594.672     2397295.471      612532.005
     2397418.545      612547.033     2397589.442      612467.061
      2397699.51      612452.103     2397818.327      612358.772
     2397923.131      612212.965     2398100.193      612079.261
      2398147.53      611924.828     2398292.336      611684.075
     2398326.079      611424.204     2398386.338      611374.067

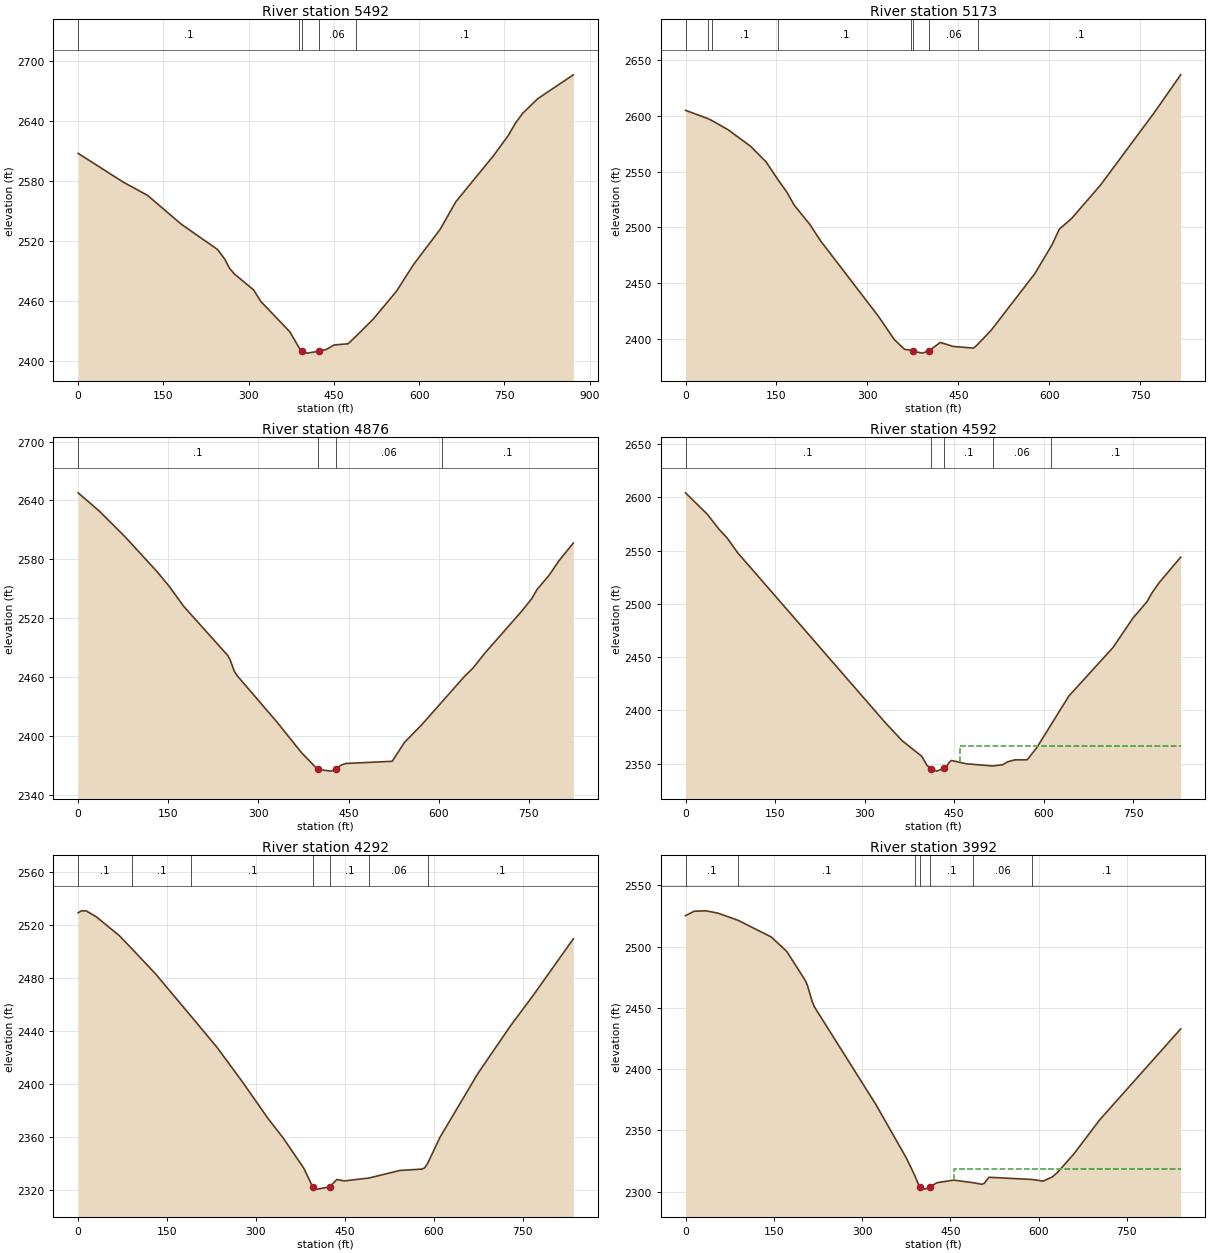
Type RM Length L Ch R = 1 ,5492    ,318.9,318.9,318.9
XS GIS Cut Line= 3
      2394012.63      613557.603     2393875.252      613175.663
2393712.91679323612739.357483655
#Sta/Elev= 30
       0 2607.78    79.4 2578.96   121.9  2565.8   181.4  2536.9   245.2 2511.59
   257.9 2501.98   266.4 2492.77   274.9 2487.06   308.9 2471.01   321.7 2459.41
   372.5 2429.16  388.782413.227   394.4  2409.8   402.5 2407.81   423.8 2409.66
   436.6 2411.43   450.4 2415.95     475 2417.19  488.292424.352   518.9 2441.64
   560.4 2469.93   590.2 2496.47   637.1 2531.75   664.6 2559.31   731.1 2605.52
   756.7 2625.43   769.5 2637.93   782.3 2647.87   808.8 2662.48   871.4 2686.37
#Mann= 5 ,-1 , 0
       0      .1       0  388.78     .06       0   394.4    .045       0
   423.8     .06       0  488.29      .1       0
Bank Sta=394.4,423.8
XS Rating Curve= 0 ,0
Exp/Cntr=0.3,0.1

Type RM Length L Ch R = 1 ,5173    ,302.8,297,284.5
XS GIS Cut Line= 3
 2394044.3366459613500.9875337112394204.98832127 613025.31149035
     2394197.209      612710.798
#Sta/Elev= 30
       0 2605.21    37.62597.611   42.882596.196    69.8 2587.92   107.7 2572.75
     133 2558.82  152.832542.634   166.9 2531.94   179.5 2519.87   204.9  2502.9
   222.6 2488.13   318.3 2420.16   344.2 2399.45   361.1 2390.65  372.732389.564
     376 2388.81   390.6 2387.16   401.1 2389.09   420.2 2396.78   441.3 2393.21
   475.1 2391.66  482.682395.424   504.5 2407.92   576.1  2458.5   604.5  2484.4
   616.5 2498.49   636.5 2507.88   684.5 2538.08   772.6 2602.69   816.7 2637.06
#Mann= 8 ,-1 , 0
       0      .1       0    37.6     .12       0   42.88      .1       0
  152.83      .1       0  372.73     .06       0     376    .045       0
   401.1     .06       0  482.68      .1       0
Bank Sta=376,401.1
XS Rating Curve= 0 ,0
Exp/Cntr=0.3,0.1

Type RM Length L Ch R = 1 ,4876    ,283.6,284.1,283.2
XS GIS Cut Line= 2
     2394519.831       613507.21     2394357.083       612699.48
#Sta/Elev= 30
       0 2647.75    35.2 2629.13    77.9 2603.07   130.9 2567.66   150.6 2553.17
   175.8 2531.92   249.1 2481.83   253.3  2476.9   259.6 2466.24   264.7 2461.29
   331.2 2413.81   371.6 2382.95   398.5 2365.85   420.6 2364.05   428.3 2365.83
   436.9 2369.99   445.1 2371.84   522.6 2374.08     543 2393.31   571.6 2411.25
  605.462434.661   642.9 2460.65   657.3 2469.32     677 2484.47   738.9 2527.68
   755.2 2540.14   763.4 2549.06   783.8 2563.77   800.1 2578.51     824 2596.56
#Mann= 4 ,-1 , 0
       0      .1       0   398.5    .045       0   428.3     .06       0
  605.46      .1       0
Bank Sta=398.5,428.3
XS Rating Curve= 0 ,0
Exp/Cntr=0.3,0.1

Type RM Length L Ch R = 1 ,4592    ,301.8,300,296.5
XS GIS Cut Line= 3
2394816.60310298613466.162529389     2394711.078      613058.944
     2394623.013      612659.937
#Sta/Elev= 30
       0 2604.14    36.4 2584.11    56.7 2569.57    69.5 2561.89    87.1 2548.08
   333.9 2388.85   362.9 2371.42   395.9 2356.72   404.2 2348.45   411.1 2345.26
   420.7  2342.9     433 2345.56   437.1 2346.92   441.2 2350.86   445.3 2352.92
   469.9 2349.83  514.612347.718   531.3 2348.94   539.5 2351.67   551.9  2353.5
   572.3 2353.54   588.7  2365.3  612.332386.562   641.9  2413.3   715.7 2458.75
   749.8 2486.82     773 2502.01   781.2 2510.17   793.5 2519.93   829.3 2543.76
#Mann= 5 ,-1 , 0
       0      .1       0   411.1    .045       0     433      .1       0
  514.61     .06       0  612.33      .1       0
#XS Ineff= 2 , 0
                          460.01         2366.67
Permanent Ineff=
       F       F
Bank Sta=411.1,433
XS Rating Curve= 0 ,0
Exp/Cntr=0.3,0.1

Type RM Length L Ch R = 1 ,4292    ,292.8,300,305.6
XS GIS Cut Line= 3
     2395153.147      613379.547     2394999.395       613001.55
     2394854.424      612599.356
#Sta/Elev= 30
       0 2529.52     5.4 2530.97    13.7 2530.92    30.9 2526.35    69.9    2512
   90.762502.225   130.3  2483.4  190.972450.951   233.9 2427.86   277.1 2401.58
   320.3 2373.84   346.2 2358.87   380.7 2336.22   393.7 2323.94  396.62 2321.92
     398 2320.66   404.4  2320.3   424.7 2322.04   436.4 2327.58   449.2 2326.52
  490.912328.717   542.7 2334.41     581  2335.5   585.2 2336.65  590.262340.254
   610.7 2359.62   674.5  2407.8   729.4 2443.79   768.1  2467.1   835.6 2509.78
#Mann= 7 ,-1 , 0
       0      .1       0   90.76      .1       0  190.97      .1       0
  396.62    .045       0   424.7      .1       0  490.91     .06       0
  590.26      .1       0
Bank Sta=396.62,424.7
XS Rating Curve= 0 ,0
Exp/Cntr=0.3,0.1

Type RM Length L Ch R = 1 ,3992    ,302.6,300,294.9
XS GIS Cut Line= 3
     2395233.593      613365.525     2395262.766      612961.292
     2395285.655       612525.54
#Sta/Elev= 30
       0 2525.21    14.7 2528.81    34.7 2529.15    54.8  2527.3   89.092521.476
   145.7 2507.83   171.9 2496.14   203.2 2472.63   207.2 2468.35   215.2 2455.26
   219.2 2450.66   323.5 2371.12   375.6 2327.18  389.33 2313.44   397.8 2303.87
   407.5 2301.99  415.82 2304.01   427.7 2307.27   455.8 2309.33  489.052307.238
   503.8 2305.94   507.8 2306.78   515.8 2311.67   588.72309.879     608 2308.54
   623.5 2311.97     632 2315.46     660 2330.68   704.1 2358.62   841.6 2432.76
#Mann= 7 ,-1 , 0
       0      .1       0   89.09      .1       0  389.33      .1       0
   397.8    .045       0  415.82      .1       0  489.05     .06       0
   588.7      .1       0
#XS Ineff= 2 , 0
                          456.77         2318.11
Permanent Ineff=
       F       F
Bank Sta=397.8,415.82
XS Rating Curve= 0 ,0
Exp/Cntr=0.3,0.1

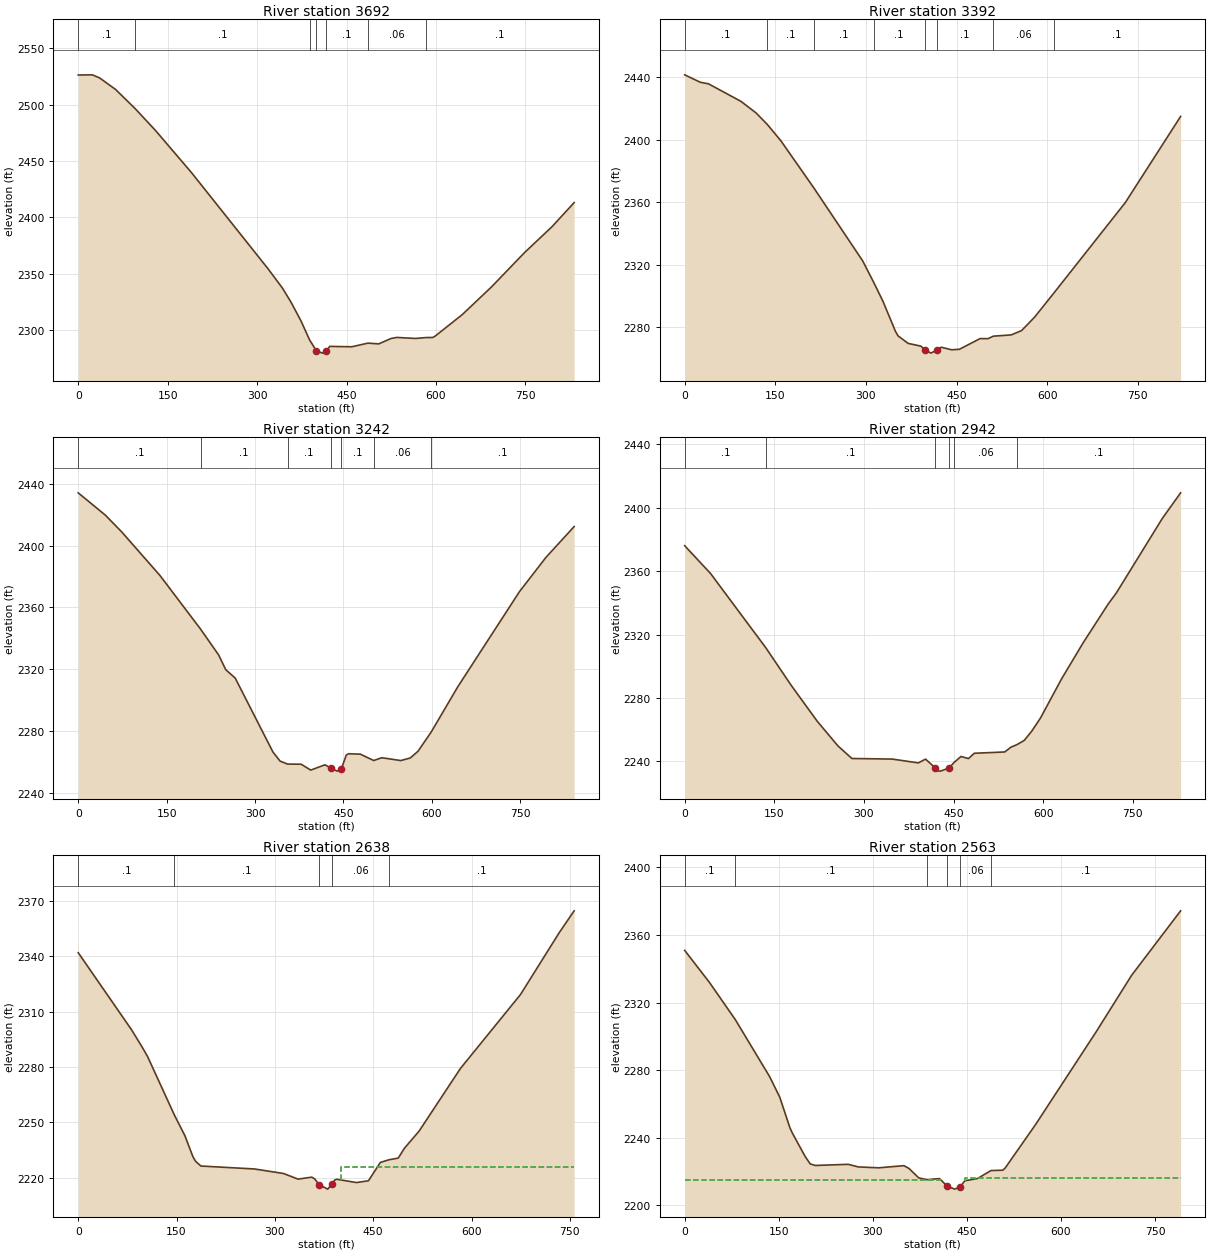
Type RM Length L Ch R = 1 ,3692    ,300.6,300,297.7
XS GIS Cut Line= 3
      2395619.91      613314.198     2395549.632      612913.541
      2395451.55      612499.975
#Sta/Elev= 30
       0 2526.28    23.7 2526.46    35.8 2523.75    62.6 2513.53   95.452496.511
   129.3 2477.29   190.2  2439.6   318.3 2354.48   342.5 2337.31   356.7    2325
   373.6 2308.23   388.1 2291.32   399.32281.756   409.5  2279.6  416.13 2281.53
   421.8 2285.58   458.8 2285.23  485.872288.459     504 2287.79   524.6 2292.57
   534.3 2293.53   565.7 2292.61  583.712293.413   594.5 2293.47   598.6 2294.66
     644  2313.7   693.2 2338.34   748.6 2368.79   794.5 2391.67   831.8 2413.12
#Mann= 7 ,-1 , 0
       0      .1       0   95.45      .1       0   388.1      .1       0
   399.3    .045       0  416.13      .1       0  485.87     .06       0
  583.71      .1       0
Bank Sta=399.3,416.13
XS Rating Curve= 0 ,0
Exp/Cntr=0.3,0.1

Type RM Length L Ch R = 1 ,3392    ,147.1,150,153.8
XS GIS Cut Line= 3
      2395941.26      613184.618     2395821.655      612792.864
     2395673.312      612409.509
#Sta/Elev= 30
       0 2441.63    25.8 2436.87    39.4 2435.87    93.1 2424.63   118.2 2417.19
  136.82  2409.8   159.3  2399.3  213.962369.024   294.6 2322.36  312.482308.863
     328 2296.59   348.9 2277.14   353.1 2274.33   369.8 2269.49   390.8 2267.74
   397.5 2265.42   407.5 2263.25   417.7 2265.33   424.6 2267.03   441.7  2265.4
   454.6  2265.7   488.9 2272.58   501.8 2272.52  510.852274.122   540.4 2274.93
   557.5 2277.69     579 2286.28  610.682301.632   729.1  2359.7   820.7 2414.96
#Mann= 8 ,-1 , 0
       0      .1       0  136.82      .1       0  213.96      .1       0
  312.48      .1       0   397.5    .045       0   417.7      .1       0
  510.85     .06       0  610.68      .1       0
Bank Sta=397.5,417.7
XS Rating Curve= 0 ,0
Exp/Cntr=0.3,0.1

Type RM Length L Ch R = 1 ,3242    ,305.3,300,291.7
XS GIS Cut Line= 3
     2395982.884      613172.804     2395959.365      612737.539
      2395914.16      612334.715
#Sta/Elev= 30
       0 2434.15      46 2419.72      74 2408.78   138.8 2380.61  207.562345.957
   238.3  2329.2   250.3 2319.69   266.3 2314.29   330.4 2266.38   342.4 2260.55
  355.152258.615   378.2 2258.52   394.5 2254.71   418.5 2258.13   428.42256.126
   438.9 2254.05   446.6 2255.66   454.7 2264.43   458.7  2265.3   478.7 2265.02
  501.362260.911   514.9 2262.73   547.2 2260.89   563.3 2262.56   576.4 2266.89
  598.972279.455   643.8 2308.56   748.5 2370.18   793.5  2392.4   841.3 2412.31
#Mann= 7 ,-1 , 0
       0      .1       0  207.56      .1       0  355.15      .1       0
   428.4    .045       0   446.6      .1       0  501.36     .06       0
  598.97      .1       0
Bank Sta=428.4,446.6
XS Rating Curve= 0 ,0
Exp/Cntr=0.3,0.1

Type RM Length L Ch R = 1 ,2942    ,303.9,303.7,306.8
XS GIS Cut Line= 3
2396416.71421358613024.395233025      2396201.25       612656.17
     2395992.769      612310.915
#Sta/Elev= 30
       0 2376.13    43.5 2358.49  135.962311.633   178.1  2288.1   222.1 2265.23
   256.6 2249.76   279.8 2241.86   347.5 2241.49     391 2239.08   403.1 2241.46
   419.1 2236.01   423.5 2234.07   428.1 2233.89   442.1 2235.83  450.562239.264
   462.4 2243.15   474.9 2241.81   484.7 2245.16   535.6 2245.98   545.9    2249
  555.972250.603   568.3 2253.29   580.9 2259.17   595.5 2267.45   630.4 2291.89
   666.4 2314.61   708.5 2339.21   722.5 2346.39   799.4  2393.4   829.9 2409.48
#Mann= 6 ,-1 , 0
       0      .1       0  135.96      .1       0   419.1    .045       0
   442.1      .1       0  450.56     .06       0  555.97      .1       0
Bank Sta=419.1,442.1
XS Rating Curve= 0 ,0
Exp/Cntr=0.3,0.1

Type RM Length L Ch R = 1 ,2638    ,66.1,74.7,85.3
XS GIS Cut Line= 3
2396438.94129384612951.1018769262396497.71854883612623.958852246
2396295.62357289 612250.94141481
#Sta/Elev= 30
       0 2341.97    81.5 2300.11    97.8 2290.65   105.9 2285.62  146.872253.872
   162.8 2242.74     175 2231.39     179 2228.93   187.2 2226.33   268.7 2224.74
   313.1 2222.29   335.4 2219.24   356.3  2220.3   360.9 2219.33   367.4 2216.26
   380.6 2213.81   386.92216.414   391.4 2218.78   394.4 2219.16   424.6 2217.37
   442.8 2218.35     461 2228.29  473.972229.709   488.3 2230.64   497.4 2235.84
   520.1 2245.28   583.2 2279.24   674.8  2319.3   733.7 2352.73   756.6 2364.64
#Mann= 5 ,-1 , 0
       0      .1       0  146.87      .1       0   367.4    .045       0
   386.9     .06       0  473.97      .1       0
#XS Ineff= 2 , 0
                          400.84         2225.57
Permanent Ineff=
       F       F
Bank Sta=367.4,386.9
XS Rating Curve= 0 ,0
Exp/Cntr(USF)=0,0
Exp/Cntr=0.5,0.3

Type RM Length L Ch R = 1 ,2563    ,31.7,32.1,31
XS GIS Cut Line= 3
2396478.10804305612965.0901152782396550.61351504612450.800099537
2396518.02891539612181.368837393
#Sta/Elev= 30
       0 2350.84    39.5 2331.92    80.82309.878   135.5 2276.18   151.7 2263.98
   167.8 2245.98   171.9  2242.7   192.1 2228.99   200.2  2224.6   208.2 2223.67
   260.8 2224.35   276.9 2222.81   309.2 2222.28   349.6 2223.55   357.7  2221.9
   373.3  2216.3  386.53  2215.3   406.3 2215.92   418.3 2211.58   430.4 2209.68
   439.2 2210.97   446.6 2214.61   466.8 2215.93  488.442220.665   507.2 2220.87
   511.2 2222.24   559.6 2247.92   656.3  2302.8   712.7 2336.13   790.8 2374.24
#Mann= 6 ,-1 , 0
       0      .1       0    80.8      .1       0  386.53     .06       0
   418.3    .045       0   439.2     .06       0  488.44      .1       0
#XS Ineff= 2 , 0
          410.85    2215   446.8            2216
Permanent Ineff=
       F       F
Bank Sta=418.3,439.2
XS Rating Curve= 0 ,0
Exp/Cntr=0.5,0.3

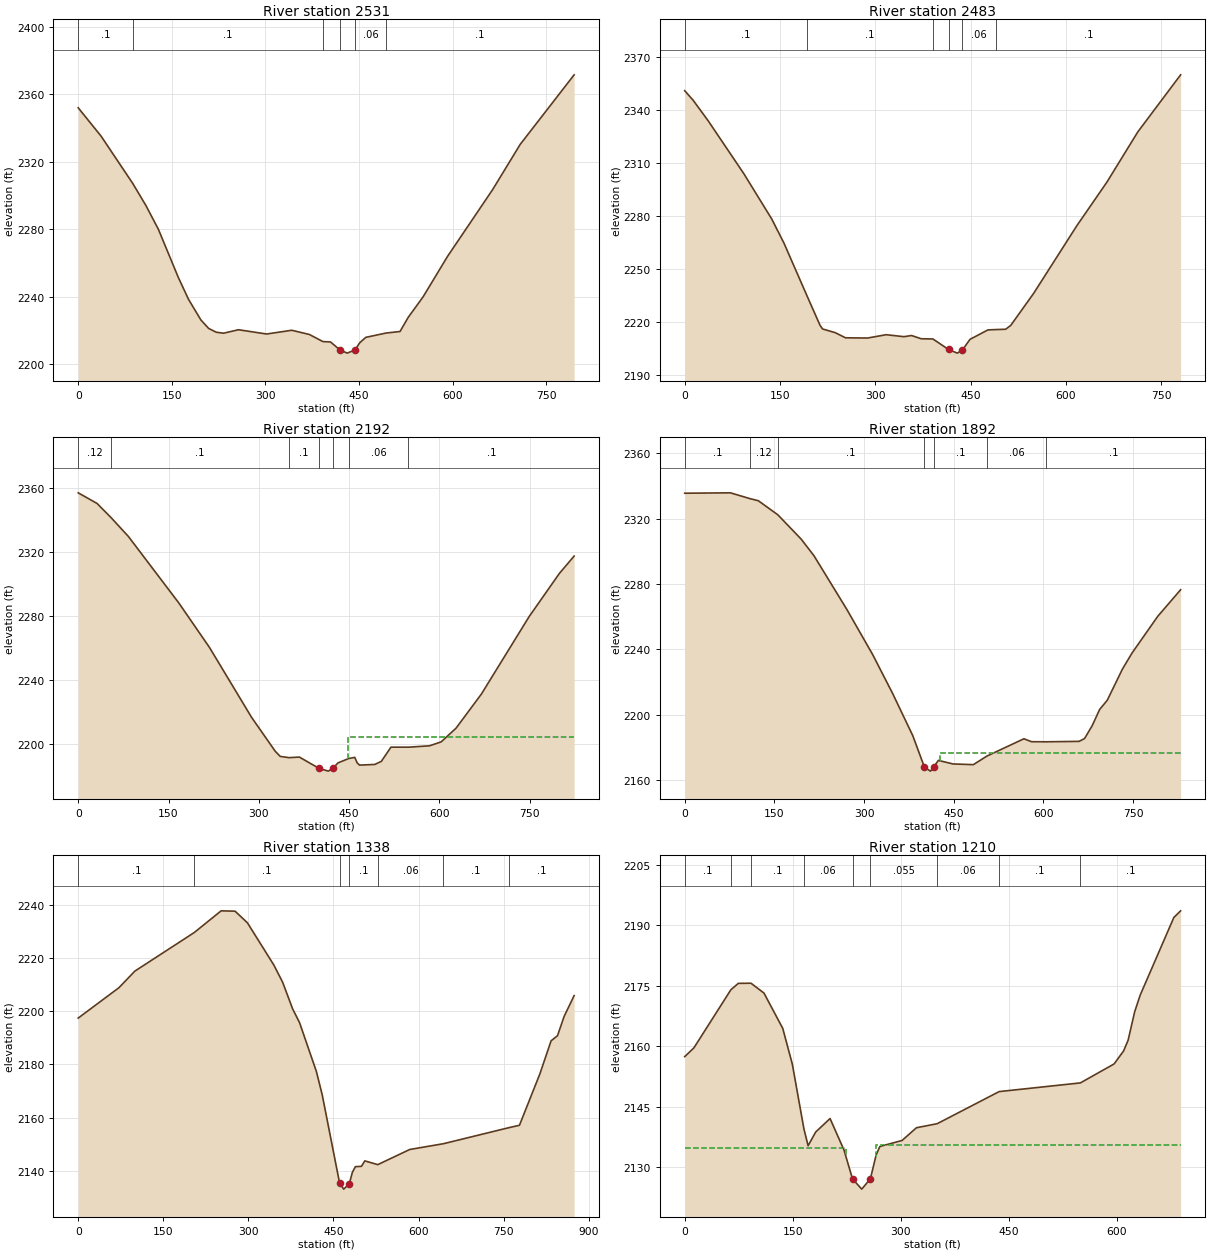
Type RM Length L Ch R = 1 ,2531    ,50.7,48.5,46.9
XS GIS Cut Line= 3
2396512.98208388612966.2425582922396580.39351147612448.408062997
2396558.18477659612176.865697347
#Sta/Elev= 30
       0 2351.89    36.7 2335.07   87.312307.103   108.5 2293.95   128.4 2279.93
   160.7 2251.09   176.8 2238.32   196.6  2226.1   209.1 2221.07   221.2 2218.83
     233 2218.26   256.9 2220.31   301.9 2217.77   342.2    2220   370.5 2217.49
  392.072213.293   404.3 2213.06   419.2 2208.42     431 2206.44   443.6 2208.33
   451.1 2212.57   460.9  2215.8  493.662218.365   515.7 2219.26   528.8 2227.63
   552.7 2239.82   591.9 2263.83   664.2 2303.44   708.3 2330.21   794.7 2371.44
#Mann= 6 ,-1 , 0
       0      .1       0   87.31      .1       0  392.07     .06       0
   419.2    .045       0   443.6     .06       0  493.66      .1       0
Bank Sta=419.2,443.6
XS Rating Curve= 0 ,0
Exp/Cntr=0.5,0.3

Type RM Length L Ch R = 1 ,2483    ,291.5,290.9,290.8
XS GIS Cut Line= 2
 2396605.9641117612959.7793644662396626.56568519612179.606733314
#Sta/Elev= 30
       0 2350.82    13.3 2345.41    36.9 2333.79    92.9 2303.89   136.9 2278.17
   156.3 2264.39  192.372234.662     213 2217.87     217 2215.81     237  2213.7
     253 2210.81   287.8 2210.67     317 2212.56     345 2211.44     357  2212.1
     372 2210.28  390.652210.133   415.2 2204.18     429 2202.12     437 2203.86
     449 2209.94   477.1 2215.27   489.82215.473   505.1 2215.65   513.1 2217.84
   549.1 2235.98   617.1 2274.32   664.4 2299.01   713.1 2327.51   780.4 2359.82
#Mann= 6 ,-1 , 0
       0      .1       0  192.37      .1       0  390.65     .06       0
   415.2    .045       0     437     .06       0   489.8      .1       0
Bank Sta=415.2,437
XS Rating Curve= 0 ,0
Exp/Cntr(USF)=0,0
Exp/Cntr=0.3,0.1

Type RM Length L Ch R = 1 ,2192    ,302.5,300,295.1
XS GIS Cut Line= 3
     2396901.643       612974.16     2396898.366      612559.051
      2396915.28      612150.934
#Sta/Elev= 30
       0  2357.1    31.3 2350.46   54.382341.678    83.3 2329.85   167.3 2288.15
   218.1  2260.4   287.9 2216.78   327.3 2195.53   335.5 2192.36  350.132191.563
   367.3 2191.94  399.37    2185   415.3 2183.15   423.2 2184.92   431.3 2188.27
     4492191.005   459.3 2191.75   463.3 2188.31   467.3 2186.91   492.5 2187.32
   503.4 2189.24   519.4 2198.13  548.432198.121   583.4 2198.97   602.8 2201.44
   627.5    2210   669.7 2231.38     749  2279.8   799.1 2306.71   823.6 2317.56
#Mann= 7 ,-1 , 0
       0     .12       0   54.38      .1       0  350.13      .1       0
  399.37    .045       0   423.2      .1       0     449     .06       0
  548.43      .1       0
#XS Ineff= 2 , 0
                          447.64         2204.42
Permanent Ineff=
       F       F
Bank Sta=399.37,423.2
XS Rating Curve= 0 ,0
Exp/Cntr=0.3,0.1

Type RM Length L Ch R = 1 ,1892    ,559.2,553.8,548.6
XS GIS Cut Line= 3
      2397322.59      612963.164     2397188.148      612576.883
2397052.54719809612178.742749506
#Sta/Elev= 30
       0 2335.47    76.5 2335.71  109.362332.134   123.1 2330.89  155.852322.252
   195.1 2307.28   216.3  2297.2   271.4 2264.28   314.3 2236.86   347.6 2213.14
   381.5 2187.19   401.1 2167.82   411.1 2165.45   416.4 2167.87   424.3 2172.01
   449.1 2169.83   482.9 2169.42  505.832174.703   567.5 2185.24   580.1 2183.45
  604.862183.393   659.9 2183.66   668.9  2185.4   681.6 2193.21   694.2  2203.2
   706.9 2208.83   732.3 2227.89   748.3 2237.69   791.4 2260.19   829.6 2276.42
#Mann= 7 ,-1 , 0
       0      .1       0  109.36     .12       0  155.85      .1       0
   401.1    .045       0   416.4      .1       0  505.83     .06       0
  604.86      .1       0
#XS Ineff= 2 , 0
                          426.68         2176.75
Permanent Ineff=
       F       F
Bank Sta=401.1,416.4
XS Rating Curve= 0 ,0
Exp/Cntr=0.3,0.1

Type RM Length L Ch R = 1 ,1338    ,142.2,128.2,112.3
XS GIS Cut Line= 3
2397872.31675856612876.9762601992397800.38808363612551.688319013
2397443.05844657 612145.23275727
#Sta/Elev= 30
       0 2197.36    71.8 2208.76    99.9    2215  204.782229.512     252 2237.64
   276.6  2237.5   298.3 2233.15   344.9 2217.28   360.4 2210.83     378 2200.83
   390.2 2195.66   419.9 2177.31   430.1 2168.63  460.83 2135.39   468.1 2133.11
     478 2135.16   483.3 2139.39   488.7 2141.56   499.3 2141.66   505.3 2143.72
  528.13 2142.31   584.5    2148  643.762150.162  759.392156.198   777.9 2157.09
   813.9 2176.38   833.7 2188.82     845 2190.73   856.6 2197.95   874.3 2205.79
#Mann= 7 ,-1 , 0
       0      .1       0  204.78      .1       0  460.83    .045       0
     478      .1       0  528.13     .06       0  643.76      .1       0
  759.39      .1       0
Bank Sta=460.83,478
XS Rating Curve= 0 ,0
Exp/Cntr=0.5,0.3

Type RM Length L Ch R = 1 ,1210    ,54.9,58.3,64.3
XS GIS Cut Line= 4
2397953.17670276612522.546125383 2397881.2210597612366.936511058
2397690.84366296612369.0302427912397484.84344729612115.171391156
#Sta/Elev= 30
       0 2157.41    12.8  2159.6    64.12174.021    74.5 2175.62   92.072175.656
   110.1 2173.21   136.2 2164.43   149.5 2155.54  165.552139.505   171.4 2135.28
   181.9 2138.68   201.9 2142.04   221.3 2134.19   233.12127.028   245.9  2124.5
   257.9 2127.06   265.9 2132.99   271.1 2135.09   301.9 2136.59   321.9 2139.75
  350.732140.756  436.71 2148.73  549.582150.888   596.4  2155.6   609.6 2158.83
   615.9 2161.51     625 2168.57   632.5 2172.63   679.4 2191.99   688.8 2193.64
#Mann= 9 ,-1 , 0
       0      .1       0    64.1     .06       0   92.07      .1       0
  165.55     .06       0   233.1    .045       0   257.9    .055       0
  350.73     .06       0  436.71      .1       0  549.58      .1       0
#XS Ineff= 2 , 0
          223.51  2134.6   265.2          2135.5
Permanent Ineff=
       F       F
Bank Sta=233.1,257.9
XS Rating Curve= 0 ,0
Exp/Cntr=0.5,0.3

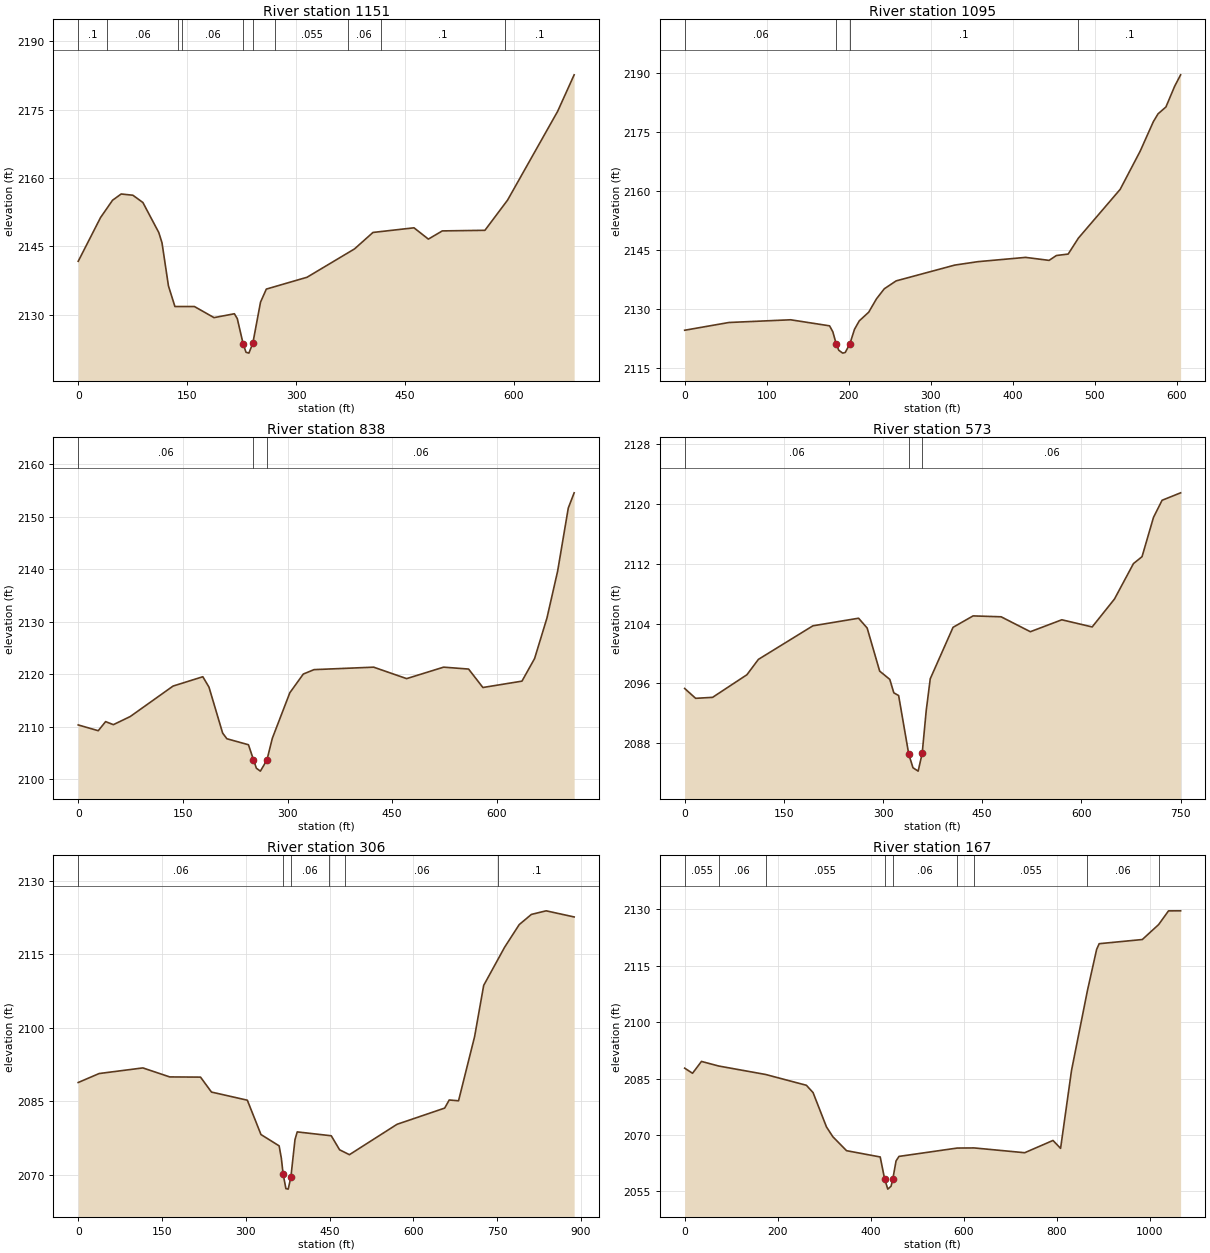
Type RM Length L Ch R = 1 ,1151    ,48.7,56.2,63.3
XS GIS Cut Line= 4
2397974.30950035 612486.545441472397893.02113324612320.555177504
 2397697.3673778612325.9506987752397523.66914227612078.191231099
#Sta/Elev= 30
       0 2141.75    30.8 2151.36    47.3 2155.15    59.2 2156.52    75.3 2156.25
    89.1 2154.65     111 2148.06   115.4 2145.82   124.3 2136.35   133.2 2131.83
     160 2131.83   187.1 2129.39   215.1 2130.24   219.1 2129.18   227.1 2123.68
   231.1 2121.79   235.1  2121.6   240.52123.754   251.1 2132.78   259.1 2135.65
   315.2 2138.25   380.6 2144.47     406 2148.08   462.5  2149.1   482.3 2146.62
   501.5 2148.42   560.2 2148.55   591.4 2155.18   660.3 2174.64   683.1 2182.67
#Mann= 10 ,-1 , 0
       0      .1       0   40.32     .06       0  137.42      .1       0
  142.45     .06       0   227.1    .045       0   240.5     .06       0
  271.14    .055       0  371.35     .06       0  416.61      .1       0
  587.61      .1       0
Bank Sta=227.1,240.5
XS Rating Curve= 0 ,0
Exp/Cntr=0.5,0.3

Type RM Length L Ch R = 1 ,1095    ,257.1,257.6,258.7
XS GIS Cut Line= 2
2398030.96386373612377.1962795662397523.68778648612048.025158372
#Sta/Elev= 30
       0 2124.57    53.9 2126.54   129.2 2127.23   176.7 2125.69   180.6  2124.2
  184.94    2121   187.9 2119.48   192.7 2118.75   195.8 2118.92   201.4  2121.1
   207.1 2124.82   212.9 2126.96   224.4 2129.16   233.9 2132.57   243.4 2135.11
   257.8 2137.12   329.3 2141.14   357.5 2142.01   415.7  2143.1   444.3 2142.34
   453.3 2143.58   467.6 2143.94  480.062147.995     531  2160.4   555.4 2170.11
   571.5 2177.63   577.2 2179.61   586.8 2181.35   597.5 2186.65 604.717 2189.53
#Mann= 4 ,-1 , 0
       0     .06       0  184.94    .045       0   201.4      .1       0
  480.06      .1       0
Bank Sta=184.94,201.4
XS Rating Curve= 0 ,0
Exp/Cntr(USF)=0,0
Exp/Cntr=0.3,0.1

Type RM Length L Ch R = 1 ,838     ,268.6,264.9,261
XS GIS Cut Line= 2
2398273.20434019612275.2804657162397716.14230243611833.784548947
#Sta/Elev= 30
       0 2110.36    28.7 2109.26    39.3 2110.99    50.4 2110.41    74.6 2111.96
   135.9 2117.75   178.6 2119.53   187.4 2117.56     207 2108.81   213.1 2107.73
     244 2106.59  251.13 2103.77   255.4 2102.11   261.1 2101.57  270.46 2103.68
   278.2 2107.81   303.3 2116.48   322.6 2120.04     338 2120.88   423.4 2121.35
   470.7 2119.17   523.7 2121.35   559.5 2120.99     580 2117.48     636 2118.69
   654.1 2122.99   671.8 2130.69   687.1  2139.6   702.4 2151.63710.8001 2154.52
#Mann= 3 ,-1 , 0
       0     .06       0  251.13    .045       0  270.46     .06       0
Bank Sta=251.13,270.46
XS Rating Curve= 0 ,0
Exp/Cntr(USF)=0,0
Exp/Cntr=0.3,0.1

Type RM Length L Ch R = 1 ,573     ,268.1,266.6,263.8
XS GIS Cut Line= 2
2398497.71936778612009.2341300792397804.80955143611722.082314294
#Sta/Elev= 30
       0 2095.29    16.6 2093.97    42.2  2094.1    94.1 2097.13   111.5 2099.19
   193.9 2103.69     263 2104.71     276 2103.39   294.9 2097.62   310.2 2096.51
   316.3 2094.71   323.6 2094.34  338.92 2086.47   345.3 2084.66   353.1 2084.21
   359.2 2086.58   365.3 2092.32   371.4 2096.59   405.9 2103.49   436.2 2105.02
   478.6  2104.9   522.8  2102.9   570.4  2104.5   616.3 2103.54     650 2107.28
   678.7 2112.03   691.7 2112.96     709 2118.22     722 2120.52750.0535 2121.52
#Mann= 3 ,-1 , 0
       0     .06       0  338.92    .045       0   359.2     .06       0
Bank Sta=338.92,359.2
XS Rating Curve= 0 ,0
Exp/Cntr(USF)=0,0
Exp/Cntr=0.3,0.1

Type RM Length L Ch R = 1 ,306     ,139.8,139.7,139.2
XS GIS Cut Line= 4
2398565.54599421611873.3899368572398418.18776821611665.766921897
2398005.11814557611594.5882581082397808.27327033611678.166656191
#Sta/Elev= 30
       0 2088.84    37.4 2090.67   115.7 2091.82   163.8 2089.98   218.9 2089.94
   238.5 2086.89   302.7 2085.23   327.1 2078.22   359.6 2075.91   363.6 2073.36
   366.72070.184   371.7 2067.19   375.8 2067.08   380.62069.494     388 2077.21
     392 2078.76   452.9 2077.97   467.8 2075.11   485.4 2074.11   570.6 2080.31
   655.9 2083.62     664 2085.27   680.7 2085.11   709.4 2098.19   725.7 2108.66
   763.2 2116.46   789.3 2121.07   811.1 2123.15   837.5 2123.88   887.6 2122.63
#Mann= 6 ,-1 , 0
       0     .06       0   366.7    .045       0   380.6     .06       0
  449.04    .055       0  477.51     .06       0  752.07      .1       0
Bank Sta=366.7,380.6
XS Rating Curve= 0 ,0
Exp/Cntr(USF)=0,0
Exp/Cntr=0.3,0.1

Type RM Length L Ch R = 1 ,167     ,64.3,64.3,64.3
XS GIS Cut Line= 4
2398591.01268239611808.9950325052398398.35109142611518.742140956
2398006.38508259611466.371494516 2397754.4681899611668.565598796
#Sta/Elev= 30
       0 2087.77    16.9 2086.41    36.1 2089.56    72.8 2088.35   174.1 2086.09
   261.8 2083.22   276.2 2081.27     305 2072.15   318.7 2069.54   348.2 2065.83
   420.6 2064.16   429.92058.435   436.9 2055.61     444 2056.39   447.72058.306
   454.7 2063.11     461 2064.31   586.4 2066.53   622.9 2066.56   731.4 2065.29
   792.3 2068.55   808.6 2066.45   832.1 2087.15   866.3 2108.36   886.2 2119.37
   891.6 2120.86   984.4 2121.97  1019.4 2125.93  1040.8 2129.59  1066.8  2129.6
#Mann= 9 ,-1 , 0
       0    .055       0    72.8     .06       0   174.1    .055       0
   429.9    .045       0   447.7     .06       0   586.4    .055       0
   622.9    .055       0   866.3     .06       0  1019.4      .1       0
Bank Sta=429.9,447.7
XS Rating Curve= 0 ,0
Exp/Cntr(USF)=0,0
Exp/Cntr=0.3,0.1

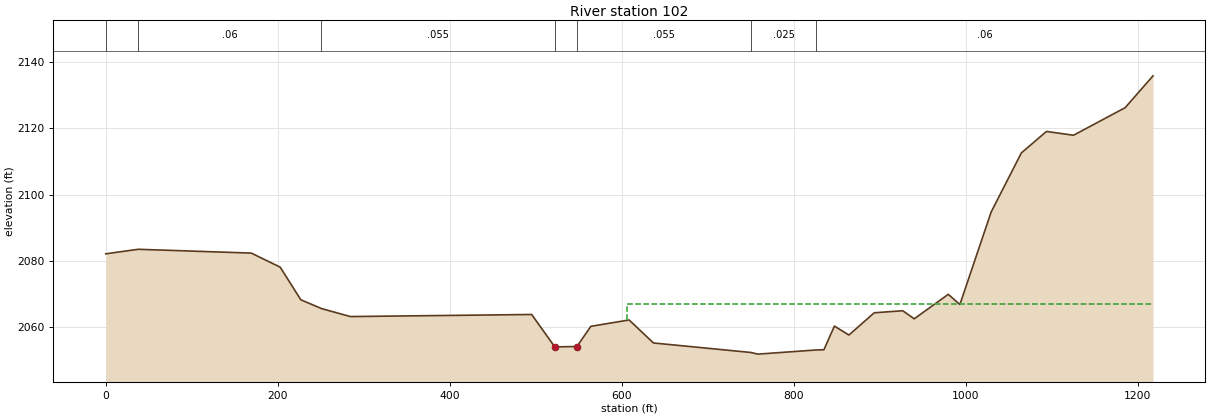
Type RM Length L Ch R = 1 ,102     ,,,
XS GIS Cut Line= 4
2398669.95221059611803.7617177242398442.95367152611462.284586032
  2397997.762634611394.869093315 2397712.5632132 611610.27928644
#Sta/Elev= 30
       0 2082.09    37.6 2083.46   169.2 2082.31   202.8 2078.06   226.8  2068.2
   250.8 2065.55   284.4 2063.13   495.2 2063.76   522.1 2053.96   547.8 2054.08
     564 2060.18   608.5  2062.1   636.8 2055.15   750.1 2052.28   758.2 2051.78
   825.8 2053.03     835  2053.1   847.2 2060.25   864.1 2057.55   893.5 2064.27
   926.7 2064.89     940 2062.45   979.6 2069.85   993.1 2066.77  1029.5 2094.75
  1064.6 2112.59  1093.8 2119.07  1125.2 2117.92  1185.2 2126.24  1217.7 2135.88
#Mann= 7 ,-1 , 0
       0    .055       0    37.6     .06       0   250.8    .055       0
   522.1    .045       0   547.8    .055       0   750.1    .025       0
   825.8     .06       0
#XS Ineff= 2 , 0
                          606.44            2067
Permanent Ineff=
       F       F
Bank Sta=522.1,547.8
XS Rating Curve= 0 ,0
Exp/Cntr(USF)=0,0
Exp/Cntr=0.3,0.1
LCMann Table=0

Chan Stop Cuts=-1
Use User Specified Reach Order=0
Composite Channel Slope=5